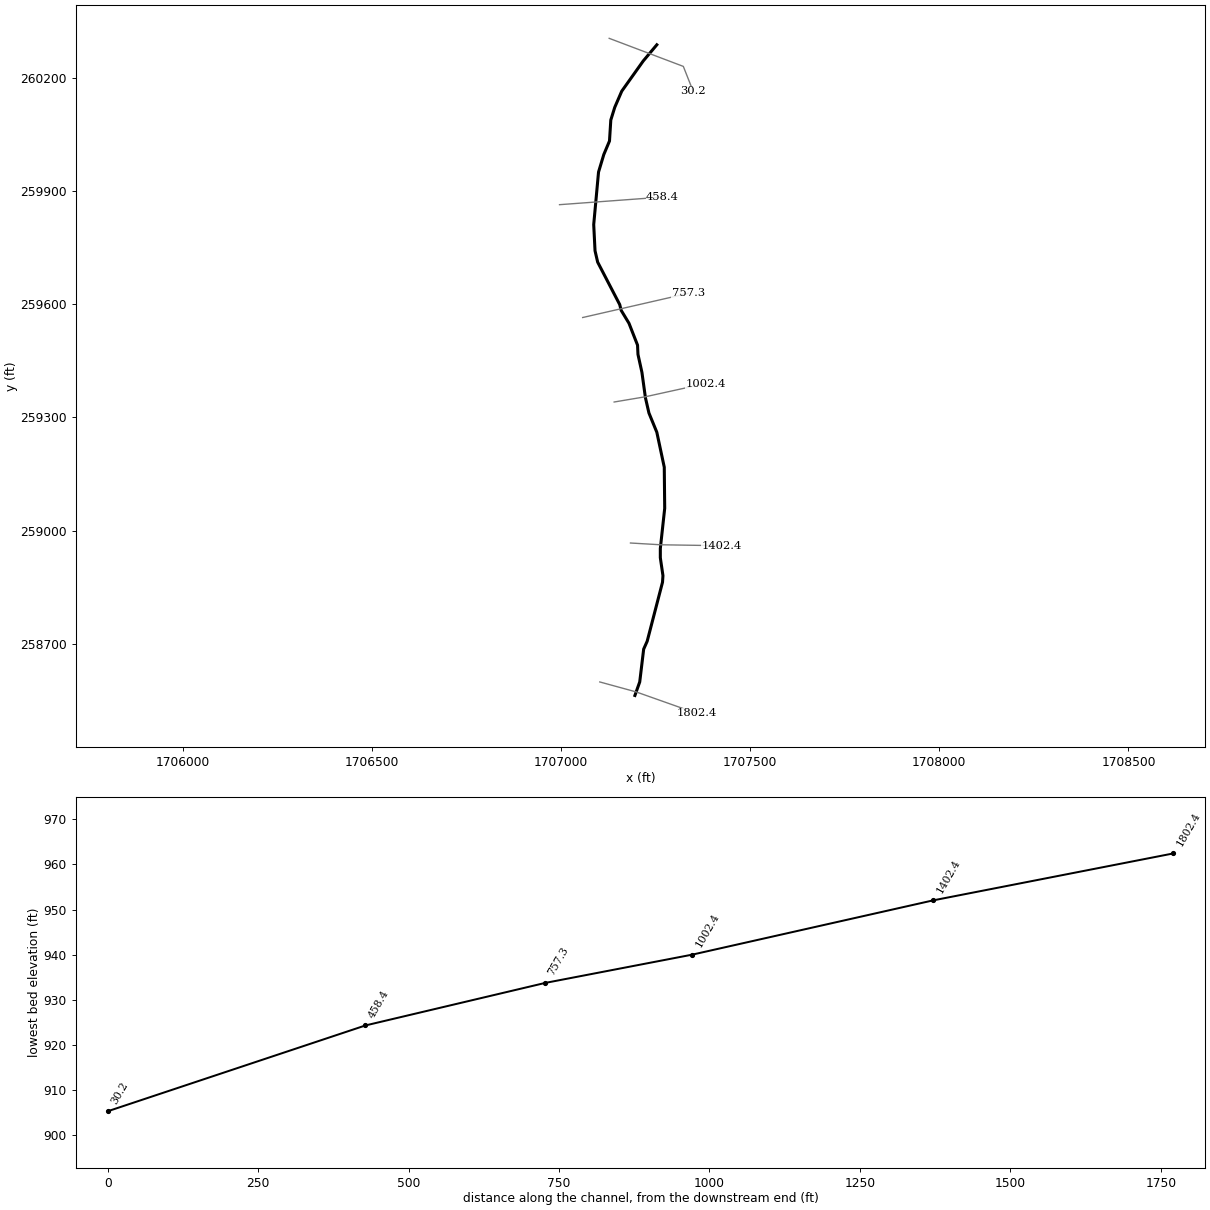
--- LEFTHNDFRK.prj (project) ---

Proj Title=LEFTHNDFRK
Current Plan=p01
Default Exp/Contr=0,0
English Units
Geom File=g01
Flow File=f01
Plan File=p01
BEGIN DESCRIPTION:
END DESCRIPTION:
DSS Export Rating Curves= 0
DSS Export Rating Curve Sorted= 0
DSS Export Volume Flow Curves= 0
DXF OffsetX= 0
DXF OffsetY= 0
DXF ScaleX= 0
DXF ScaleY= 0

--- LEFTHNDFRK.p01 (plan) ---

Plan Title=Floodplain
Program Version=4.00
Geom File=g01
Flow File=f01
K Sum by GR=0
Std Step Tol=0.01
Critical Tol=0.01
Num of Std Step Trials=20
Max Error Tol=0.3
Flow Tol Ratio=0.001
Split Flow NTrial=30
Split Flow Tol=0.02
Split Flow Ratio=0.02
Log Output Level=0
Friction Slope Method=1
Unsteady Friction Slope Method=2
Unsteady Bridges Friction Slope Method=1
Global Log Level=0
CheckData=False
Run HTab=0
Run UNet=0
Run PostProcess=0
UNET Theta=0
UNET Theta Warmup=0
UNET ZTol=0
UNET ZSATol=0
UNET MxIter=0
UNET MaxInSteps=0
UNET DtIC=0
UNET DtMin=0
UNET MaxCRTS=0
UNET WFStab=0
UNET SFStab=0
UNET WFX=0
UNET SFX=0
UNET DSS MLevel=0
UNET DZMax Abort=0
UNET Convert EG Bridges=0
UNET Use Existing IB Tables=0
UNET Froude Limit=0
UNET Froude Power=0
Write IC File=0
Echo Input=False
Echo Output=False
Write Detailed=0

--- LEFTHNDFRK.f01 (steady flow) ---

Flow Title=NFF Regression Equation
Program Version=4.00
Number of Profiles=1
Profile Names=P100yr
River Rch & RM=LEFTHNDFRK,Main      ,1802.4
987.8857
River Rch & RM=LEFTHNDFRK,Main      ,30.2
1016.146
Boundary for River Rch & Prof#=LEFTHNDFRK,Main      ,1
Up Type=0
Dn Type=3
Dn Slope=0.033196

--- LEFTHNDFRK.g01 (geometry) ---

Geom Title=USGS 10m DEM
Program Version=4.10

River Reach=LEFTHNDFRK      ,Main
Reach XY= 30
     1707195.513      258563.446     1707208.254      258599.351
     1707218.677      258686.216     1707227.943      258707.064
      1707268.48      258863.421     1707269.638      258880.794
     1707262.689      258928.281     1707262.689      258952.603
     1707274.271      259059.157     1707273.113      259168.029
     1707253.424      259260.685     1707232.576      259311.646
      1707223.31      259352.183     1707214.045      259419.359
     1707203.621      259466.845     1707202.481      259491.353
     1707179.912      259549.171     1707159.176      259583.549
     1707155.357      259598.829     1707097.066      259711.226
     1707090.117      259741.339     1707086.642      259810.831
     1707099.383      259949.816     1707113.281      259996.144
     1707128.338      260032.048     1707131.812      260087.642
     1707142.236       260121.23     1707160.767      260164.083
     1707217.519      260243.999     1707253.424      260286.853

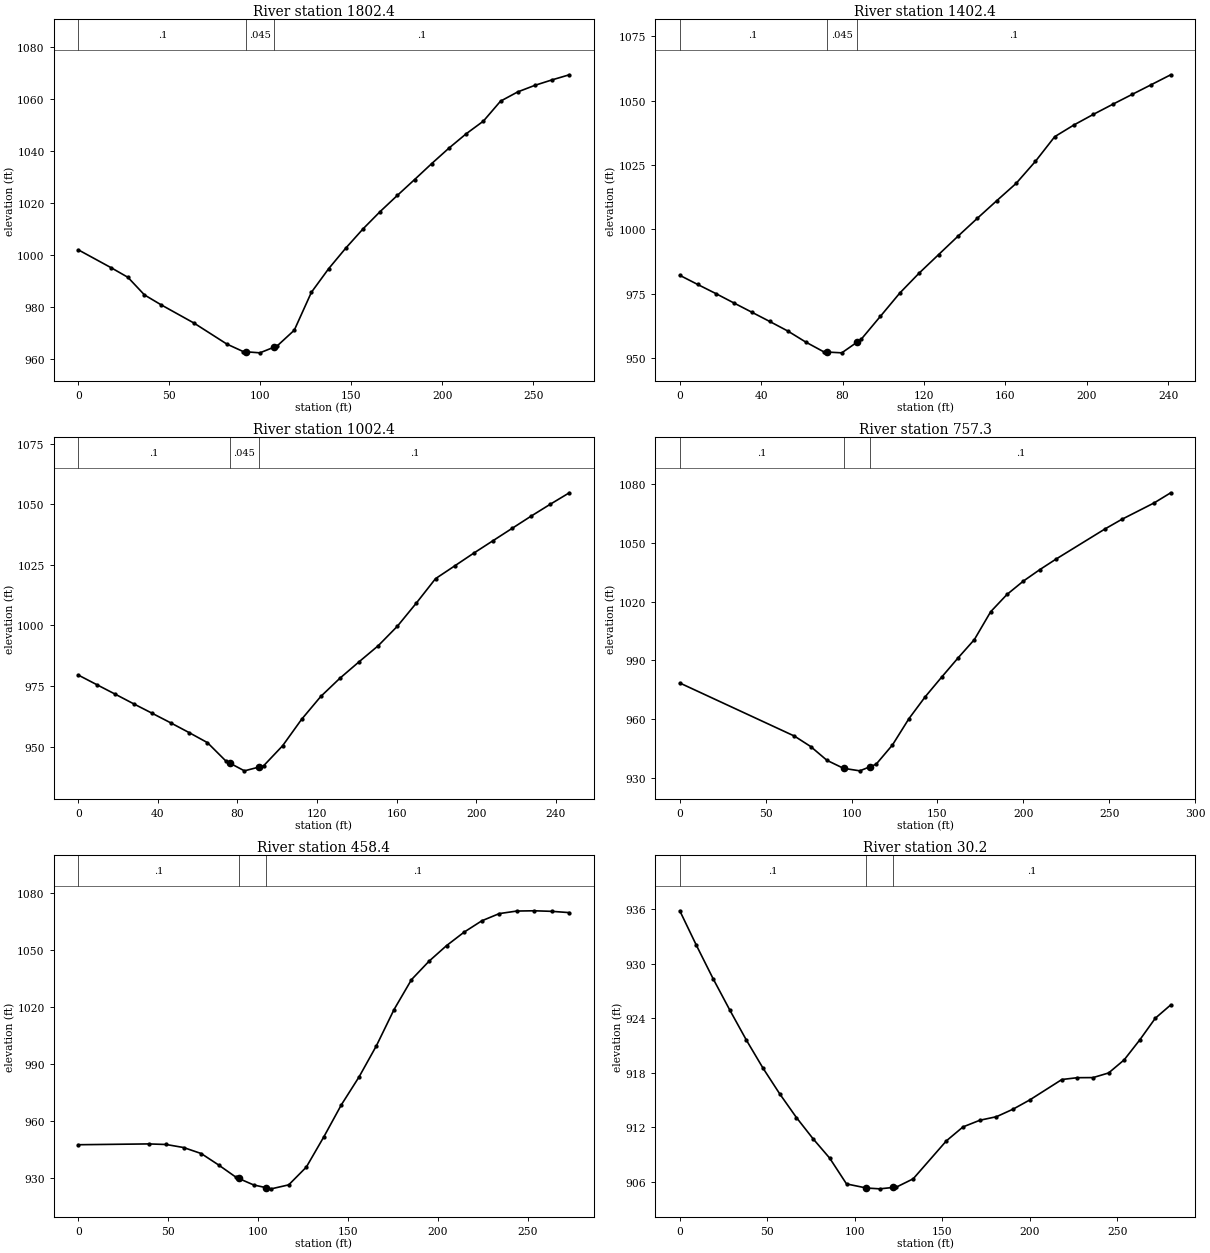
Type RM Length L Ch R = 1 ,1802.4  ,395,399.7,407.1
XS GIS Cut Line= 3
     1707102.701      258599.269     1707198.857      258572.871
     1707359.025      258516.037
#Sta/Elev= 29
       0 1002.02    18.1  995.12    27.2  991.48    36.3  984.71    45.3  980.97
    63.4  973.94    81.6  965.81    90.6  962.94    92.2  962.86    99.7  962.46
   107.2  964.56   109.2  965.12   118.6  971.16     128  985.72   137.5  994.81
   146.9 1002.71   156.4 1010.11   165.8 1016.76   175.2 1022.94   184.7 1029.04
   194.1 1035.18   203.6 1041.14     213 1046.61   222.5  1051.5   231.9 1059.16
   241.3  1062.7   250.8 1065.25   260.2 1067.34   269.7  1069.3
#Mann= 3 , 0 , 0
       0      .1       0    92.2    .045       0   107.2      .1       0
Bank Sta=92.2,107.2
XS Rating Curve= 0 ,0
Exp/Cntr=0.3,0.1

Type RM Length L Ch R = 1 ,1402.4  ,394.8,399.9,405.2
XS GIS Cut Line= 3
     1707183.787      258967.276     1707263.277        258962.6
     1707424.853      258960.094
#Sta/Elev= 29
       0  982.14     8.8  978.59    17.7  975.06    26.5  971.44    35.4  967.81
    44.2  964.21    53.1  960.49    61.9  956.21    70.8   952.4    72.1  952.35
    79.6  952.03    87.1  956.17    89.1  957.27    98.6  966.25   108.1  975.26
   117.6     983   127.2  990.22   136.7  997.35   146.2  1004.3   155.7 1011.11
   165.2 1017.81   174.7 1026.38   184.2 1035.99   193.7 1040.57   203.2 1044.66
   212.7 1048.57   222.2  1052.4   231.7 1056.21   241.2 1060.04
#Mann= 3 , 0 , 0
       0      .1       0    72.1    .045       0    87.1      .1       0
Bank Sta=72.1,87.1
XS Rating Curve= 0 ,0
Exp/Cntr=0.3,0.1

Type RM Length L Ch R = 1 ,1002.4  ,243.6,244.9,245.1
XS GIS Cut Line= 3
     1707140.672      259340.747     1707222.977      259354.596
     1707382.606      259389.746
#Sta/Elev= 29
       0  979.51     9.3  975.55    18.6  971.61    27.8  967.66    37.1  963.76
    46.4  959.82    55.6  955.82    64.9  951.64    74.2  944.03      76  943.25
    83.5     940      91  941.59    93.1  942.04   102.7  950.35   112.3  961.31
   121.9   970.7   131.5  978.21   141.2  985.04   150.8  991.65   160.4  999.67
     170 1009.29   179.6 1019.32   189.2 1024.56   198.8 1029.84   208.5 1034.98
   218.1 1040.07   227.7 1045.14   237.3 1050.03   246.9 1054.77
#Mann= 3 , 0 , 0
       0      .1       0      76    .045       0      91      .1       0
Bank Sta=76,91
XS Rating Curve= 0 ,0
Exp/Cntr=0.3,0.1

Type RM Length L Ch R = 1 ,757.3   ,301.9,298.5,295.1
XS GIS Cut Line= 2
     1707057.499      259564.505      1707336.03      259628.445
#Sta/Elev= 24
       0  978.48    66.7  951.44    76.2   946.1    85.7  939.05    95.3     935
    95.8  934.93   104.8  933.71   110.8  935.83   114.3  937.07   123.8  946.88
   133.4   960.3   142.9  971.48   152.4  981.42   161.9  991.15   171.5 1000.61
     181 1014.81   190.5 1023.61     200  1030.4   209.6 1036.26   219.1 1041.66
   247.7 1057.07   257.2 1061.82   276.2 1070.28   285.8 1075.42
#Mann= 3 , 0 , 0
       0      .1       0    95.8    .045       0   110.8      .1       0
Bank Sta=95.8,110.8
XS Rating Curve= 0 ,0
Exp/Cntr=0.3,0.1

Type RM Length L Ch R = 1 ,458.4   ,437.7,428.1,418.6
XS GIS Cut Line= 2
      1706996.29      259863.397     1707268.675      259883.494
#Sta/Elev= 28
       0  947.51      39  947.94    48.8  947.64    58.5  946.04    68.3  942.88
      78  936.85    87.8  930.31    89.1  929.78    97.5  926.33   104.1  924.95
   107.3  924.28     117  926.38   126.8  935.74   136.6  951.78   146.3  968.57
   156.1  983.18   165.8  999.67   175.6 1018.72   185.3 1034.47   195.1 1044.21
   204.8 1052.38   214.6  1059.5   224.4 1065.44   234.1 1069.24   243.9 1070.59
   253.6 1070.73   263.4 1070.43   273.1 1069.76
#Mann= 3 , 0 , 0
       0      .1       0    89.1    .045       0   104.1      .1       0
Bank Sta=89.1,104.1
XS Rating Curve= 0 ,0
Exp/Cntr=0.3,0.1

Type RM Length L Ch R = 1 ,30.2    ,38.1,30.3,22.5
XS GIS Cut Line= 3
     1707127.547      260303.975      1707323.49      260229.653
     1707349.582      260163.547
#Sta/Elev= 30
       0  935.82     9.5  932.02      19  928.37    28.6   924.9    38.1  921.59
    47.6  918.51    57.2  915.67    66.7  913.08    76.2  910.75    85.7  908.62
    95.3  905.79   106.7  905.34   114.3  905.25   121.7   905.4   123.8  905.44
   133.4  906.35   152.4  910.53   161.9  912.06   171.5  912.79     181  913.18
   190.5  914.01     200  915.02   218.4  917.27   227.3  917.47   236.2  917.48
   245.1  917.99     254  919.43   262.9  921.62   271.8  924.01   280.6  925.47
#Mann= 3 , 0 , 0
       0      .1       0   106.7    .045       0   121.7      .1       0
Bank Sta=106.7,121.7
XS Rating Curve= 0 ,0
Exp/Cntr=0.3,0.1

Chan Stop Cuts=-1
Use User Specified Reach Order=0
Composite Channel Slope=5